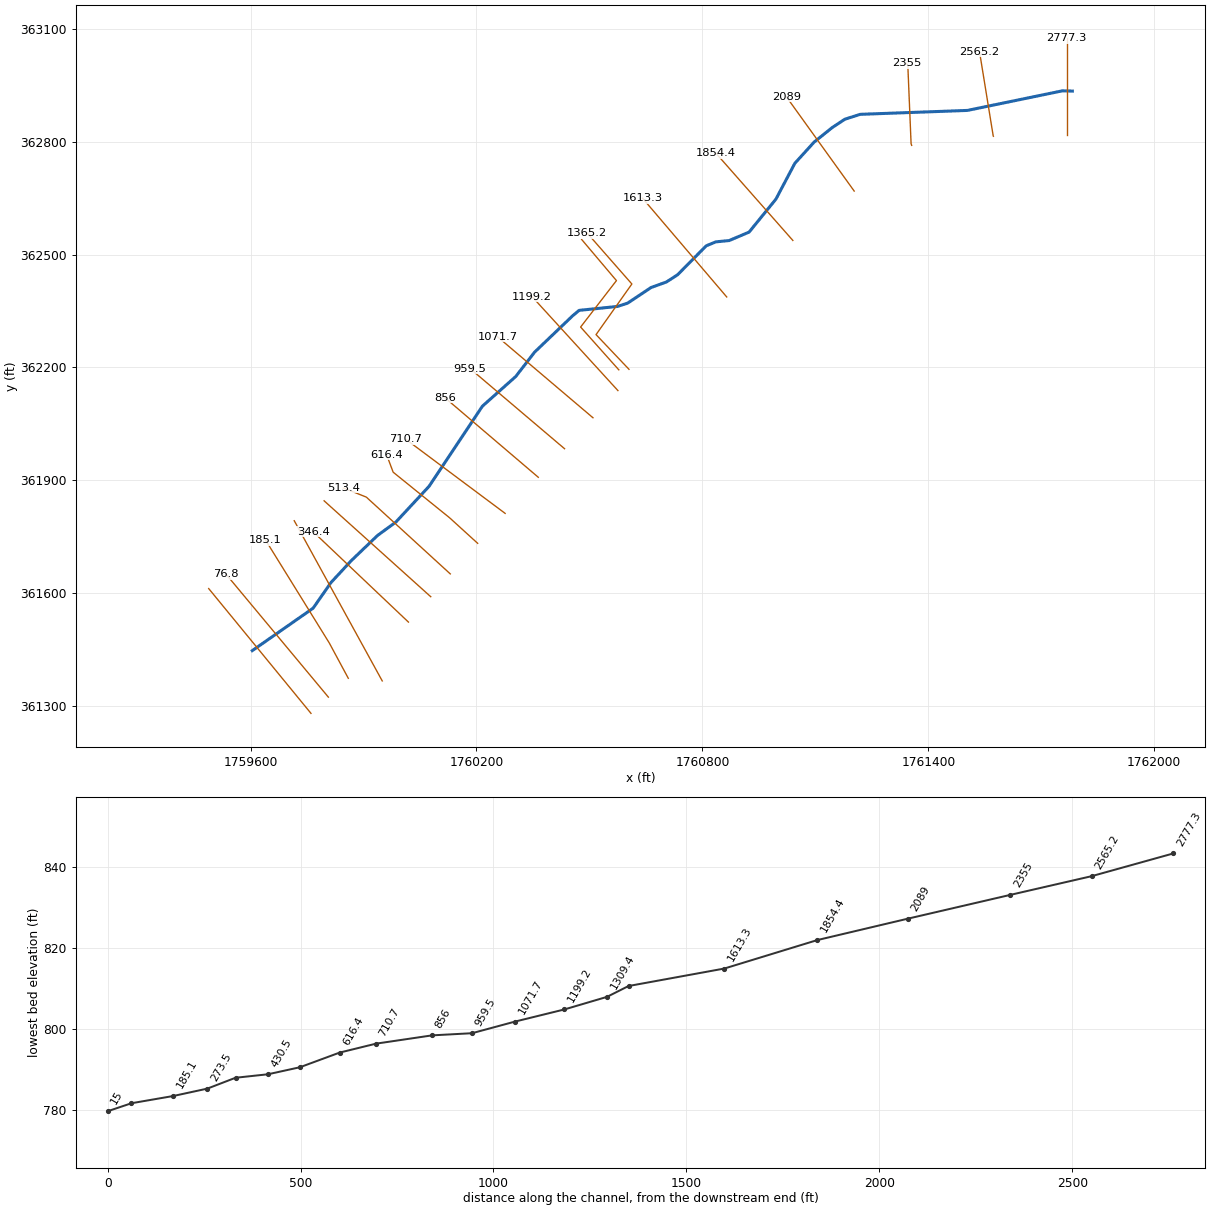
--- LICKBR.prj (project) ---

Proj Title=LICKBR
Current Plan=p01
Default Exp/Contr=0,0
English Units
Geom File=g01
Flow File=f01
Plan File=p01
BEGIN DESCRIPTION:
END DESCRIPTION:
DSS Export Rating Curves= 0
DSS Export Rating Curve Sorted= 0
DSS Export Volume Flow Curves= 0
DXF Filename=.\BACKUP\LICKBR.
DXF OffsetX= 0
DXF OffsetY= 0
DXF ScaleX= 0
DXF ScaleY= 0

--- LICKBR.p01 (plan) ---

Plan Title=Floodplain
Program Version=4.00
Geom File=g01
Flow File=f01
K Sum by GR=0
Std Step Tol=0.01
Critical Tol=0.01
Num of Std Step Trials=20
Max Error Tol=0.3
Flow Tol Ratio=0.001
Split Flow NTrial=30
Split Flow Tol=0.02
Split Flow Ratio=0.02
Log Output Level=0
Friction Slope Method=1
Unsteady Friction Slope Method=2
Unsteady Bridges Friction Slope Method=1
Global Log Level=0
CheckData=False
Run HTab=0
Run UNet=0
Run PostProcess=0
UNET Theta=0
UNET Theta Warmup=0
UNET ZTol=0
UNET ZSATol=0
UNET MxIter=0
UNET MaxInSteps=0
UNET DtIC=0
UNET DtMin=0
UNET MaxCRTS=0
UNET WFStab=0
UNET SFStab=0
UNET WFX=0
UNET SFX=0
UNET DSS MLevel=0
UNET DZMax Abort=0
UNET Convert EG Bridges=0
UNET Use Existing IB Tables=0
UNET Froude Limit=0
UNET Froude Power=0
Write IC File=0
Echo Input=False
Echo Output=False
Write Detailed=0

--- LICKBR.f01 (steady flow) ---

Flow Title=NFF Regression Equation
Program Version=4.10
Number of Profiles= 1
Profile Names=P100yr
River Rch & RM=LICKBR,Main            ,2777.3
829.0896
River Rch & RM=LICKBR,Main            ,2565.2
981.2871
River Rch & RM=LICKBR,Main            ,513.4
1018.527
River Rch & RM=LICKBR,Main            ,273.5
1026.357
Boundary for River Rch & Prof#=LICKBR,Main            , 1
Up Type= 0
Dn Type= 3
Dn Slope=0.022013
DSS Import GetInterval= 0
DSS Import GetPeak= 0
DSS Import FillOption= 0

--- LICKBR.g01 (geometry) ---

Geom Title=USGS 10m DEM
Program Version=4.10

River Reach=LICKBR          ,Main
Reach XY= 30
     1761782.465      362935.667     1761755.855       362936.21
     1761503.872      362884.133      1761219.15      362873.716
     1761178.351      362860.695     1761145.365      362838.994
     1761096.754      362799.932     1761045.539      362743.508
     1760995.192      362648.022     1760924.011      362560.348
      1760871.06      362537.779     1760835.469      362534.306
     1760810.296       362523.89     1760733.907      362446.633
     1760704.393      362427.536     1760663.594      362412.779
     1760601.094      362371.112     1760574.184      362362.432
     1760472.622      362352.015     1760456.129      362338.299
     1760354.566      362241.077     1760304.219      362175.973
     1760215.678       362096.98     1760074.184      361883.872
     1759985.643      361788.386     1759937.032      361752.796
     1759867.587      361686.042     1759813.768      361627.883
     1759766.025      361559.306     1759604.567      361446.459

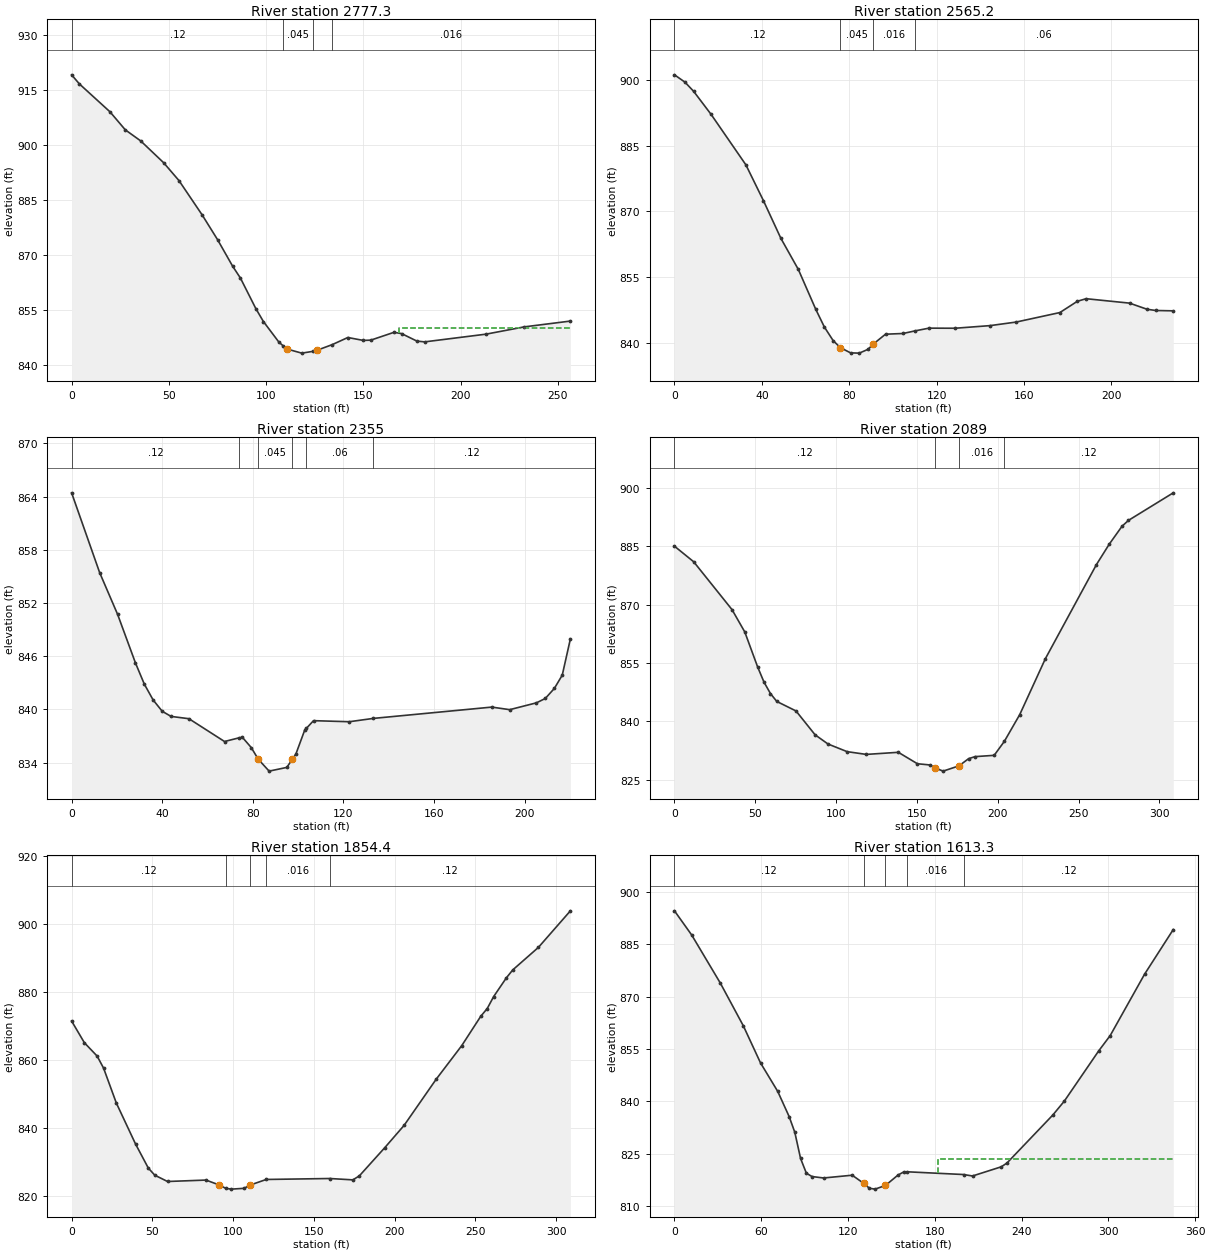
Type RM Length L Ch R = 1 ,2777.3  ,208.5,212.2,215.8
XS GIS Cut Line= 2
     1761767.291      362819.547     1761767.291      363075.958
#Sta/Elev= 30
       0  919.13       4  916.65    19.7  909.06    27.6  904.13    35.5  901.12
    47.3  895.17    55.2  890.29    67.1  880.94      75  874.21    82.8  866.93
    86.8   863.7    94.7  855.39    98.6  851.86   106.5  846.29   108.9  845.16
   110.5   844.4   118.3  843.25   123.9  843.72   126.2  844.04  133.94845.5623
     142  847.51   149.9  846.72   153.8  846.79   165.7  848.92   169.6  848.58
   177.5  846.53   181.5  846.32     213  848.42   232.7  850.41   256.4  851.99
#Mann= 4 ,-1 , 0
       0     .12       0   108.9    .045       0   123.9     .12       0
  133.94    .016       0
#XS Ineff= 2 , 0
                          168.54           850.2
Permanent Ineff=
       F       F
Bank Sta=110.5,126.2
XS Rating Curve= 0 ,0
Exp/Cntr=0.3,0.1

Type RM Length L Ch R = 1 ,2565.2  ,212.8,210.1,207.4
XS GIS Cut Line= 3
      1761572.66      362815.346     1761572.287      362816.065
     1761535.867      363040.601
#Sta/Elev= 30
       0  901.15     4.8  899.48     8.8  897.37    16.8   892.1    32.7   880.6
    40.7  872.46    48.7  863.84    56.7  856.73    64.7  847.61    68.6  843.61
    72.6  840.52    75.9   838.9    80.6   837.7    84.6  837.64    88.6  838.51
    90.9  839.67    96.6  841.96   104.6  842.12  110.11842.7189   116.5  843.34
   128.5  843.32   144.5  843.92   156.4  844.73   176.4   846.9   184.4  849.47
   188.4  850.06   208.3  849.05   216.3  847.65   220.3  847.37   228.3  847.29
#Mann= 4 ,-1 , 0
       0     .12       0    75.9    .045       0    90.9    .016       0
  110.11     .06       0
Bank Sta=75.9,90.9
XS Rating Curve= 0 ,0
Exp/Cntr=0.3,0.1

Type RM Length L Ch R = 1 ,2355    ,252.9,266.1,279.2
XS GIS Cut Line= 4
     1761355.725       362791.15     1761354.188      362795.448
     1761345.507      363003.782     1761341.567      363009.681
#Sta/Elev= 30
       0  864.43    12.4  855.42    20.3  850.73    28.2  845.24    32.1  842.86
      36  841.07      40   839.8    43.9  839.22    51.8  838.96    67.5  836.39
   74.06836.8131    75.4  836.86    79.3  835.71    82.4  834.39    87.2  833.05
      95  833.47    97.4  834.37      99  834.97   102.9  837.67  103.63837.8702
   106.8  838.74   122.6  838.62  133.19838.9948   185.5  840.27   193.4  839.98
   205.2  840.75   209.1  841.24   213.1  842.37   216.6  843.87   220.2  847.97
#Mann= 6 ,-1 , 0
       0     .12       0   74.06    .016       0    82.4    .045       0
    97.4    .016       0  103.63     .06       0  133.19     .12       0
Bank Sta=82.4,97.4
XS Rating Curve= 0 ,0
Exp/Cntr=0.3,0.1

Type RM Length L Ch R = 1 ,2089    ,232.1,234.6,236.5
XS GIS Cut Line= 2
      1761203.04      362669.538     1761023.125       362920.26
#Sta/Elev= 30
       0  885.02    11.9  881.01    35.6  868.71    43.5  862.97    51.4  854.03
    55.4  850.06    59.4  847.12    63.3   845.1    75.2  842.65      87  836.52
      95  834.15   106.8  832.19   118.7  831.48   138.5  832.02   150.3  829.08
   158.2  828.76     161  828.05   166.2  827.18     176  828.53     182  830.39
     186  830.91   197.8  831.24   204.1834.8405   213.6   841.7   229.5  856.11
   261.1  880.31     269  885.54   276.9  890.15   280.9  891.66   308.6  898.74
#Mann= 4 ,-1 , 0
       0     .12       0     161    .045       0     176    .016       0
   204.1     .12       0
Bank Sta=161,176
XS Rating Curve= 0 ,0
Exp/Cntr=0.3,0.1

Type RM Length L Ch R = 1 ,1854.4  ,241.6,241.1,241
XS GIS Cut Line= 2
     1761040.118      362538.113     1760836.081      362770.024
#Sta/Elev= 30
       0  871.47     7.9  865.08    15.8  861.14    19.8  857.58    27.7  847.29
    39.6  835.21    47.5  828.12    51.5  826.02    59.4  824.16    83.2  824.58
    91.1  823.19    95.5  822.14      99  821.91   106.9  822.15   110.5   823.1
  120.54824.7587  159.88  825.04   174.2  824.64   178.2  825.82     194  834.16
   205.9   840.7   225.7  854.26   241.6  864.21   253.4  872.88   257.4  875.16
   261.4   878.7   269.3  884.24   273.2  886.54   289.1  893.19   308.9  903.96
#Mann= 5 ,-1 , 0
       0     .12       0    95.5    .045       0   110.5     .12       0
  120.54    .016       0  159.88     .12       0
Bank Sta=91.1,110.5
XS Rating Curve= 0 ,0
Exp/Cntr=0.3,0.1

Type RM Length L Ch R = 1 ,1613.3  ,280.6,248.1,210.1
XS GIS Cut Line= 2
     1760864.502       362387.75     1760641.065      362650.461
#Sta/Elev= 30
       0  894.51    11.9   887.6    31.7  873.85    47.6  861.63    59.5  851.01
    71.4  842.86    79.3  835.65    83.2  831.17    87.2  823.67    91.2  819.46
    95.1   818.5   103.1  818.09   122.9  818.88   130.9  816.54   134.8  815.15
   138.7   814.9   145.9  815.95   154.6  818.94   158.6  819.83  161.11819.8558
  199.89819.0754   206.1  818.66     226  821.29   229.9  822.36   261.6  836.09
   269.6  840.09   293.3  854.42   301.3  858.83   325.1  876.41   344.9  889.16
#Mann= 5 ,-1 , 0
       0     .12       0   130.9    .045       0   145.9     .12       0
  161.11    .016       0  199.89     .12       0
#XS Ineff= 2 , 0
                          181.88          823.47
Permanent Ineff=
       F       F
Bank Sta=130.9,145.9
XS Rating Curve= 0 ,0
Exp/Cntr=0.3,0.1

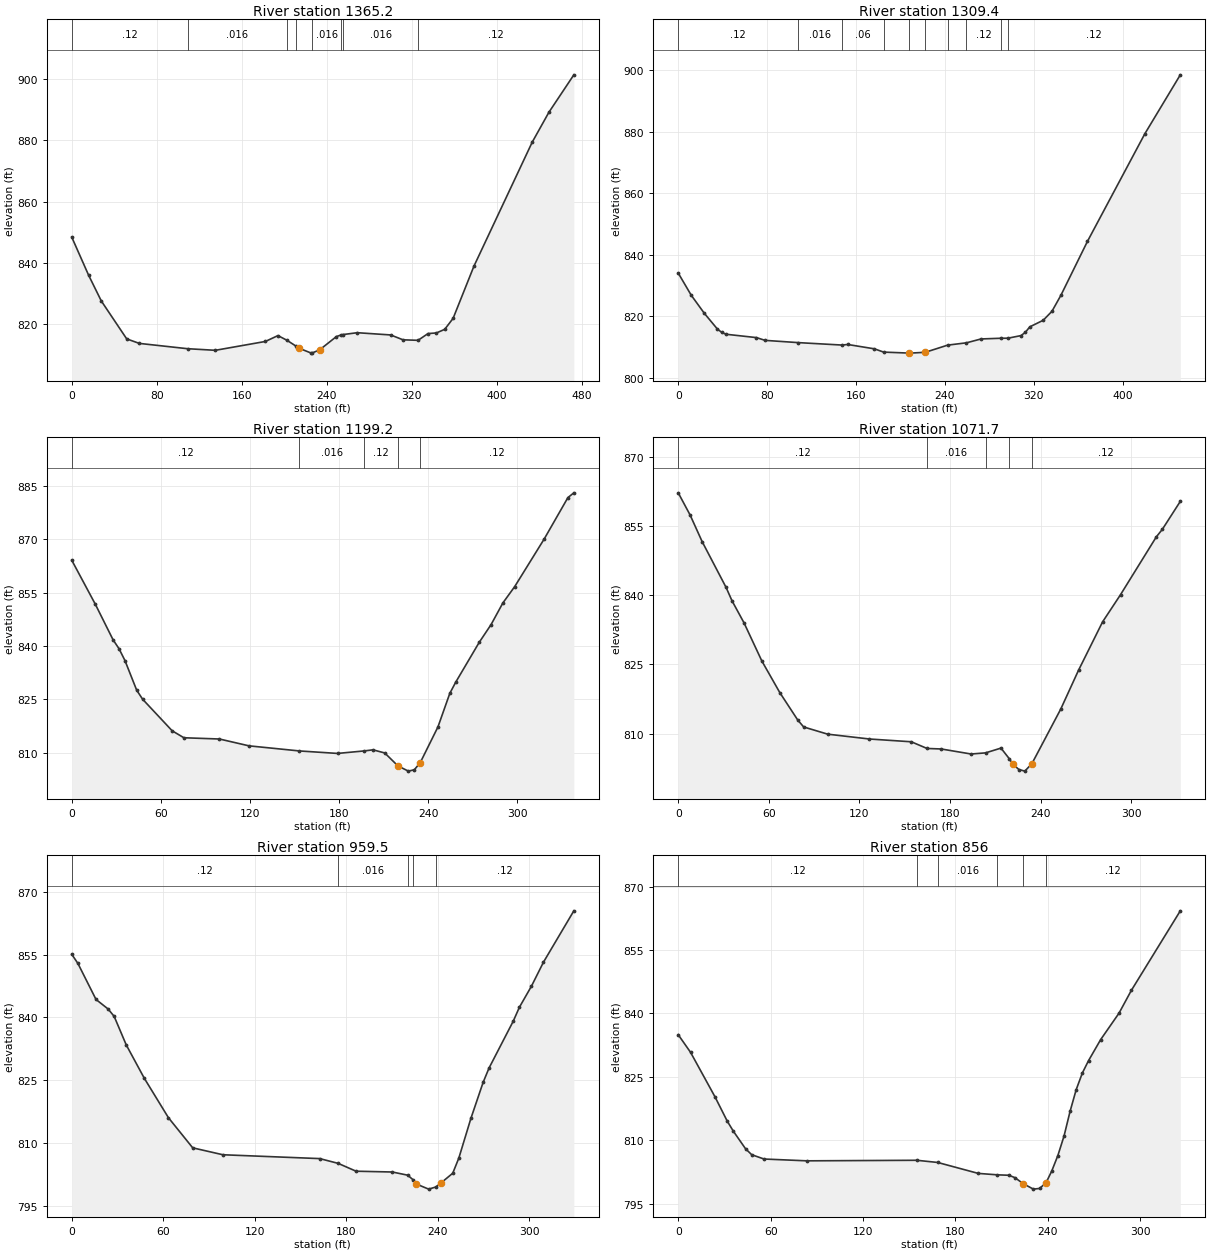
Type RM Length L Ch R = 1 ,1365.2  ,56.8,55.8,58.4
XS GIS Cut Line= 4
     1760605.008      362195.118     1760517.508      362287.479
     1760612.647      362422.202     1760493.887       362557.75
#Sta/Elev= 30
       0  848.42    15.9  835.97    27.8   827.6    51.7  815.24    63.6  813.77
  108.93812.0429   135.1  811.52   182.2  814.41     194  816.32  202.51814.7785
     211  812.88   213.6  812.23   225.4   810.6     226  810.62   233.2  811.67
     249     816  253.72816.5663   255.6816.6723   268.6  817.26     300  816.53
   311.7  814.94   325.8814.7785   335.2  816.98   343.1  817.18   350.9  818.36
   358.8  821.94   378.4  838.96   433.2  879.38   448.9  889.13   472.4  901.36
#Mann= 8 ,-1 , 0
       0     .12       0  108.93    .016       0  202.51     .12       0
     211    .045       0     226    .016       0  253.72     .12       0
   255.6    .016       0   325.8     .12       0
Bank Sta=213.6,233.2
XS Rating Curve= 0 ,0
Exp/Cntr=0.3,0.1

Type RM Length L Ch R = 1 ,1309.4  ,75.4,110.2,146.4
XS GIS Cut Line= 4
     1760577.925      362193.729     1760476.536      362307.618
     1760571.675      362431.229     1760479.234      362540.748
#Sta/Elev= 30
       0  833.97    11.7  826.76    23.5  820.87    35.2  815.78    39.1  814.69
      43  814.07    70.4  812.98    78.2  812.08  107.74811.3551  147.28810.5563
   152.5  810.74   176.5  809.33  184.85808.2629   207.3  807.95   208.5  807.93
   222.3   808.2  242.44810.5309  259.39811.2856   272.5  812.54  290.86812.7764
  296.66812.7844   308.5  813.64   312.4  814.73   316.4  816.49   328.4  818.61
   336.3  821.54   344.3  826.71   368.2  844.26   419.9   879.3   451.8  898.46
#Mann= 10 ,-1 , 0
       0     .12       0  107.74    .016       0  147.28     .06       0
  184.85     .12       0   207.3    .045       0   222.3     .12       0
  242.44    .016       0  259.39     .12       0  290.86    .016       0
  296.66     .12       0
Bank Sta=207.3,222.3
XS Rating Curve= 0 ,0
Exp/Cntr=0.3,0.1

Type RM Length L Ch R = 1 ,1199.2  ,124.6,127.5,130.4
XS GIS Cut Line= 2
     1760575.569      362138.569     1760347.828      362388.267
#Sta/Elev= 30
       0  864.06    15.9  851.67    27.8  841.72    31.8  839.22    35.8   835.9
    43.7  827.57    47.7  825.03    67.6  816.16    75.5  814.21    99.4  813.86
   119.3  811.94  153.21810.5078   178.9  809.81  197.04810.5196   202.8  810.82
   210.7  809.94   219.6   806.3   226.6  804.84   230.6  805.22   234.6  807.23
   246.5  817.24   254.5  826.68   258.4  829.76   274.3  841.01   282.3     846
   290.2  852.05   298.2  856.67   318.1  870.07     334  881.65     338  882.99
#Mann= 5 ,-1 , 0
       0     .12       0  153.21    .016       0  197.04     .12       0
   219.6    .045       0   234.6     .12       0
Bank Sta=219.6,234.6
XS Rating Curve= 0 ,0
Exp/Cntr=0.3,0.1

Type RM Length L Ch R = 1 ,1071.7  ,112.1,112.2,112.2
XS GIS Cut Line= 2
     1760509.298      362066.239     1760255.916      362281.614
#Sta/Elev= 30
       0  862.17     7.9  857.34    15.8  851.62    31.7  841.67    35.6  838.79
    43.6  833.98    55.4  825.72    67.3  818.87    79.2  812.92    83.1  811.43
      99  809.87   126.7  808.82   154.4  808.22  164.82806.7725   174.2  806.66
     194  805.57  203.58 805.815   213.8  806.85   219.3  804.55   221.7  803.34
   225.7  802.21   229.6  801.86   234.3  803.49   253.4  815.31   265.2  823.74
   281.1   834.2     293   840.1   316.7  852.62   320.7  854.26   332.6  860.32
#Mann= 5 ,-1 , 0
       0     .12       0  164.82    .016       0  203.58     .12       0
   219.3    .045       0   234.3     .12       0
Bank Sta=221.7,234.3
XS Rating Curve= 0 ,0
Exp/Cntr=0.3,0.1

Type RM Length L Ch R = 1 ,959.5   ,103.6,103.4,103.3
XS GIS Cut Line= 2
     1760433.824      361983.865      1760183.03      362197.039
#Sta/Elev= 30
       0  855.06       4   852.9    15.9  844.28    23.8  842.01    27.8  840.24
    35.7  833.44    47.6  825.43    63.4  816.03    79.3  808.84    99.1  807.19
   162.6  806.27  174.67805.1321   186.4  803.26   210.2  803.07  220.28802.3067
   223.7  801.24     226  800.19     234  798.98   238.7  799.49   241.9   800.4
   249.8  802.78   253.8  806.41   261.7  815.87   269.7  824.46   273.6  827.91
   289.5  839.12   293.5  842.42   301.4  847.45   309.3   853.2   329.2  865.45
#Mann= 5 ,-1 , 0
       0     .12       0  174.67    .016       0  220.28     .12       0
   223.7    .045       0   238.7     .12       0
Bank Sta=226,241.9
XS Rating Curve= 0 ,0
Exp/Cntr=0.3,0.1

Type RM Length L Ch R = 1 ,856     ,143.7,145.3,146.8
XS GIS Cut Line= 2
      1760364.12      361907.787     1760116.226      362119.522
#Sta/Elev= 30
       0  834.96       8   830.8    23.8  820.32    31.8  814.54    35.8  812.14
    43.7     808    47.7  806.59    55.7  805.57    83.5  805.14  154.89 805.272
  168.45804.7559   194.8  802.17  207.29801.8271   214.7  801.73   218.7  801.15
   223.8  799.78   230.6  798.45   234.6  798.61   238.8  799.94   242.5  802.71
   246.5   806.4   250.5     811   254.4  816.81   258.4  821.98   262.4  825.91
   266.4  828.83   274.3  833.82   286.2  840.06   294.2  845.44     326  864.26
#Mann= 6 ,-1 , 0
       0     .12       0  154.89     .06       0  168.45    .016       0
  207.29     .12       0   223.8    .045       0   238.8     .12       0
Bank Sta=223.8,238.8
XS Rating Curve= 0 ,0
Exp/Cntr=0.3,0.1

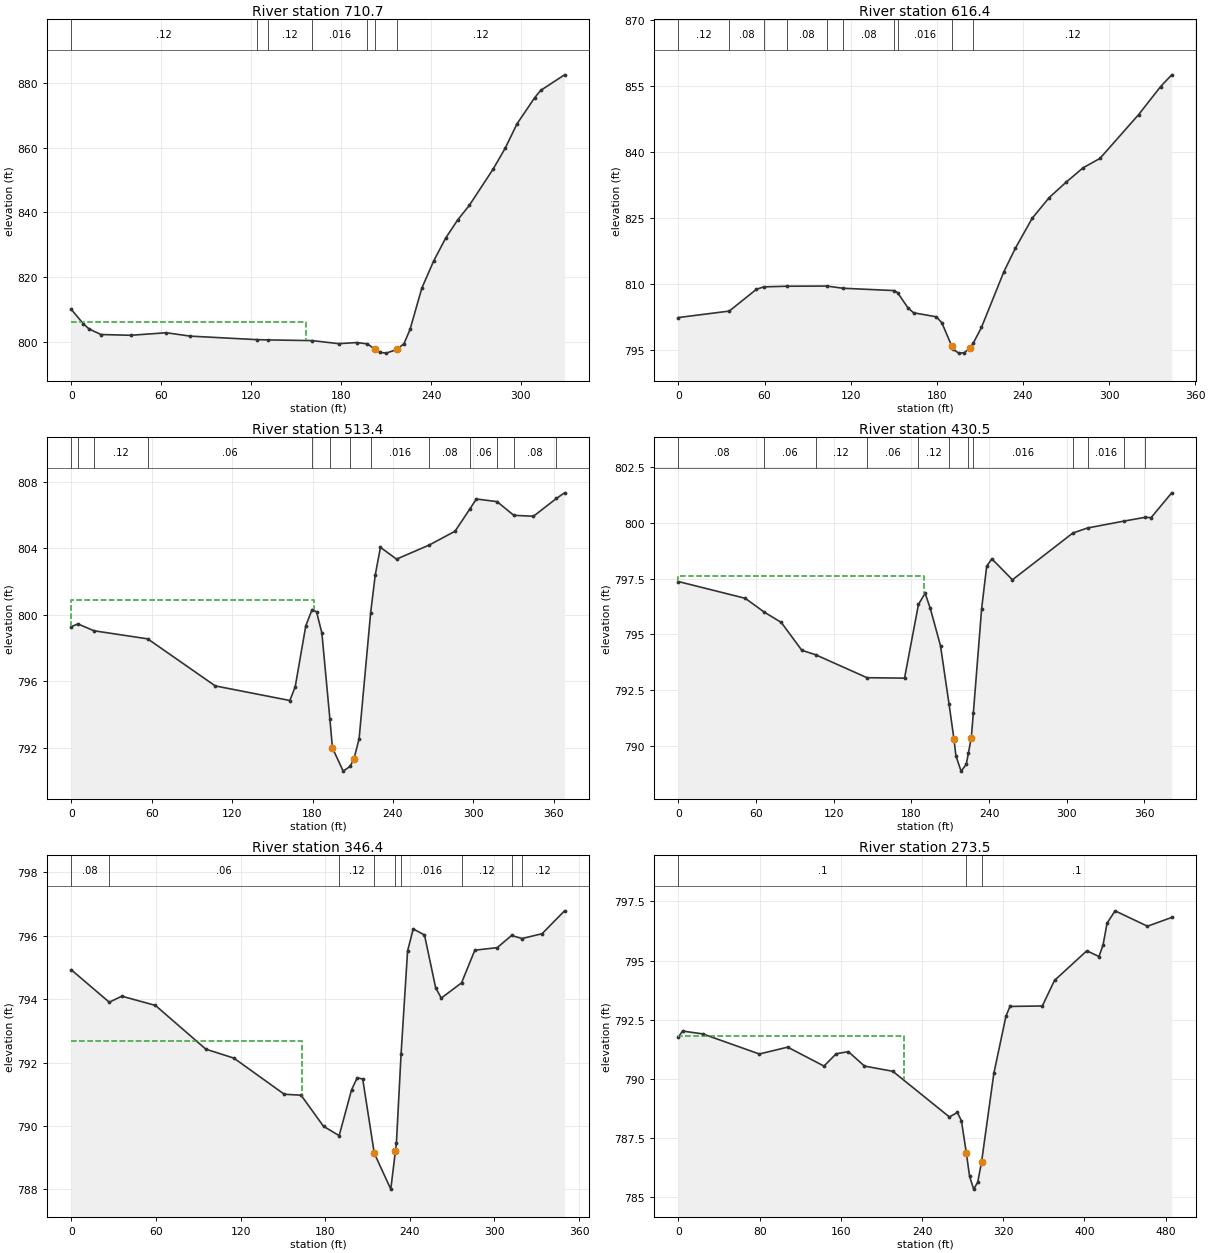
Type RM Length L Ch R = 1 ,710.7   ,95.2,94.3,93.5
XS GIS Cut Line= 2
     1760276.096      361811.716     1760012.549      362008.767
#Sta/Elev= 30
       0  809.94     7.9  805.55    11.9  803.87    19.8  802.17    39.6  801.93
    63.4  802.72    79.3  801.67  123.79800.5844  131.14 800.501  160.67800.2861
   178.4  799.34   190.3  799.68  197.54799.2794   202.3  797.71   206.2  796.62
   210.1  796.41   217.3  797.56     222  799.37     226  803.73   233.9  816.57
   241.8  824.95   249.8  832.02   257.7  837.56   265.6  842.17   281.5   853.4
   289.4  859.74   297.4  867.37   309.2  875.47   313.2  877.72   329.1  882.53
#Mann= 7 ,-1 , 0
       0     .12       0  123.79     .08       0  131.14     .12       0
  160.67    .016       0  197.54     .12       0   202.3    .045       0
   217.3     .12       0
#XS Ineff= 2 , 0
          156.32  806.17
Permanent Ineff=
       F       F
Bank Sta=202.3,217.3
XS Rating Curve= 0 ,0
Exp/Cntr=0.3,0.1

Type RM Length L Ch R = 1 ,616.4   ,104.3,103,101.7
XS GIS Cut Line= 4
     1760203.093      361732.038     1760128.619      361799.979
     1759978.679      361921.396     1759961.163      361968.165
#Sta/Elev= 30
       0  802.32   35.39 803.788    54.3  808.75   59.44809.3024   75.36  809.45
  103.44809.4876  114.62808.9895  150.38808.4536  152.63807.9996   159.9  804.54
   163.8   803.4   179.6  802.49   183.5  801.14   190.4  795.84   191.4  795.07
   195.3  794.21   199.2  794.31   203.2   795.4   205.4  796.48   211.1  800.05
   226.8  812.79   234.7  818.07   246.5  824.94   258.3  829.63   270.1  833.14
   281.9  836.41   293.7  838.56   320.6  848.52     336  854.94   343.7   857.6
#Mann= 10 ,-1 , 0
       0     .12       0   35.39     .08       0   59.44     .12       0
   75.36     .08       0  103.44     .12       0  114.62     .08       0
  150.38     .12       0  152.63    .016       0   190.4    .045       0
   205.4     .12       0
Bank Sta=190.4,203.2
XS Rating Curve= 0 ,0
Exp/Cntr=0.3,0.1

Type RM Length L Ch R = 1 ,513.4   ,82.6,82.8,82.9
XS GIS Cut Line= 3
     1760130.355      361650.674     1759907.498       361854.99
      1759846.45      361879.465
#Sta/Elev= 30
       0  799.29    4.86799.4622   16.93799.0474      57798.5612   107.4  795.73
   163.1  794.85   167.1  795.68     175  799.35  179.69800.3224     183  800.19
     187  798.91     193  793.71   194.9  791.99   202.9   790.6     208  790.88
   210.8   791.3   214.8  792.56   223.4800.1375   226.8  802.39   230.7  804.07
   242.7  803.36  267.11804.2083   286.4  805.04  297.41806.3762   302.3  806.98
  317.73  806.82  330.25805.9955   344.9  805.94  362.07807.0129   368.1  807.35
#Mann= 13 ,-1 , 0
       0     .12       0    4.86    .016       0   16.93     .12       0
      57     .06       0  179.69     .12       0     193    .045       0
     208     .12       0   223.4    .016       0  267.11     .08       0
  297.41     .06       0  317.73    .016       0  330.25     .08       0
  362.07     .06       0
#XS Ineff= 2 , 0
           180.9  800.91
Permanent Ineff=
       F       F
Bank Sta=194.9,210.8
XS Rating Curve= 0 ,0
Exp/Cntr=0.3,0.1

Type RM Length L Ch R = 1 ,430.5   ,84.7,84.1,83.5
XS GIS Cut Line= 2
     1760078.441      361589.996      1759795.29      361845.193
#Sta/Elev= 30
       0  797.37    51.6  796.62    66.2 796.005    79.4  795.54    95.3  794.29
  105.96794.0886  145.72793.0595   174.7  793.04  185.48796.3476   190.6  796.85
   194.6  796.17   202.5  794.49   209.1  791.88  212.92   790.3   214.4  789.56
   218.4  788.87   222.4  789.17   224.1  789.69   226.3  790.37   227.9 791.482
   234.3  796.16   238.2  798.06   242.2  798.39   258.1  797.45  304.76799.5463
  316.14799.7737  344.52800.0845  360.26 800.248   365.3  800.24   381.2  801.35
#Mann= 12 ,-1 , 0
       0     .08       0    66.2     .06       0  105.96     .12       0
  145.72     .06       0  185.48     .12       0   209.1    .045       0
   224.1     .12       0   227.9    .016       0  304.76     .06       0
  316.14    .016       0  344.52     .12       0  360.26    .016       0
#XS Ineff= 2 , 0
          189.89  797.61
Permanent Ineff=
       F       F
Bank Sta=212.92,226.3
XS Rating Curve= 0 ,0
Exp/Cntr=0.3,0.1

Type RM Length L Ch R = 1 ,346.4   ,81.2,73,65
XS GIS Cut Line= 2
     1760019.239      361522.435     1759765.745      361763.351
#Sta/Elev= 30
       0  794.92   26.91   793.9    35.8  794.09    59.6   793.8    95.4  792.42
   115.2  792.14     151     791   162.9  790.97   178.8  789.99   189.9789.6955
   198.7  791.14   202.7  791.52   206.6  791.48   214.8  789.14   226.5  788.01
   229.8  789.21   230.5  789.47  233.81792.2752   238.4  795.51   242.4  796.21
   250.4  796.02   258.3  794.36   262.3  794.03  276.68794.5104   286.1  795.54
     302  795.62  312.13796.0026  319.56795.9068   333.8  796.06   349.7  796.78
#Mann= 9 ,-1 , 0
       0     .08       0   26.91     .06       0   189.9     .12       0
   214.8    .045       0   229.8     .12       0  233.81    .016       0
  276.68     .12       0  312.13     .08       0  319.56     .12       0
#XS Ineff= 2 , 0
          163.69  792.67
Permanent Ineff=
       F       F
Bank Sta=214.8,229.8
XS Rating Curve= 0 ,0
Exp/Cntr=0.3,0.1

Type RM Length L Ch R = 1 ,273.5   ,85.8,88.4,90.2
XS GIS Cut Line= 2
      1759949.71      361365.819     1759716.048      361792.108
#Sta/Elev= 30
       0  791.77       4  792.02    23.9   791.9    79.7  791.05   107.6  791.34
   143.4  790.54   155.4  791.06   167.4  791.15   183.3  790.54   211.2  790.32
     267  788.39   274.9  788.58   278.9  788.22   283.7  786.86   286.9  785.88
   290.9  785.34   294.9  785.63   298.7  786.49   310.8  790.23   322.8  792.66
   326.7  793.06   358.6  793.08   370.6  794.16   402.4  795.41   414.4  795.17
   418.4  795.65   422.4  796.58   430.3   797.1   462.2  796.45   486.1  796.82
#Mann= 3 , 0 , 0
       0      .1       0   283.7    .045       0   298.7      .1       0
#XS Ineff= 2 , 0
          221.91  791.79
Permanent Ineff=
       F       F
Bank Sta=283.7,298.7
XS Rating Curve= 0 ,0
Exp/Cntr=0.3,0.1

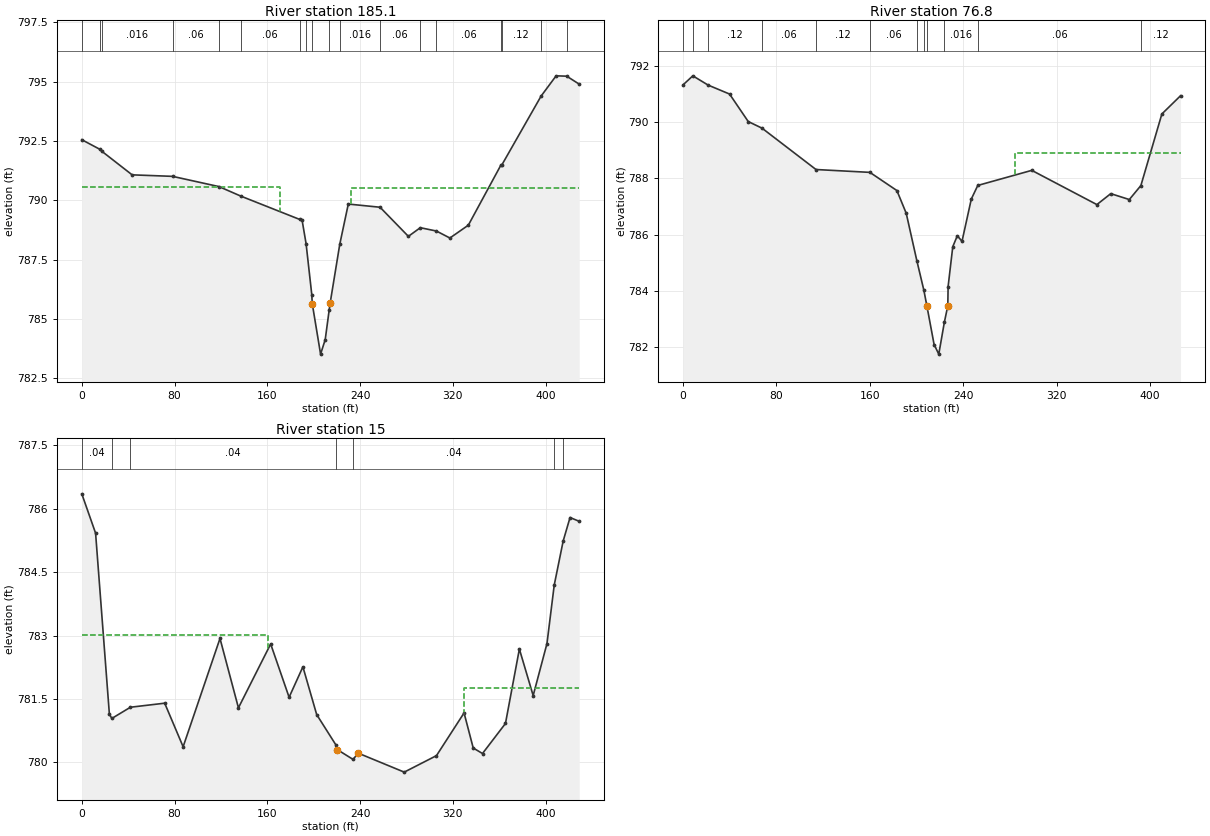
Type RM Length L Ch R = 1 ,185.1   ,105.2,108.3,111.6
XS GIS Cut Line= 3
     1759859.522      361372.896     1759809.175      361466.646
     1759639.667       361740.94
#Sta/Elev= 30
       0  792.55    15.8  792.14   17.31792.0626    43.4  791.07   78.23791.0065
   118.3790.5753  137.23790.1727  187.74789.1952     190  789.15  193.41788.1696
   198.3  786.03  198.74  785.64   205.9  783.52   209.9  784.13   213.3  785.37
  214.19  785.68  222.46788.1508   229.8  789.84  257.18789.7057   281.6  788.48
   291.9 788.844  305.77788.7042   317.4  788.41   333.3  788.95  361.35791.4774
  361.95791.4669  396.07794.3889     409  795.24  418.13795.2254   428.9  794.89
#Mann= 18 ,-1 , 0
       0    .016       0    15.8     .12       0   17.31    .016       0
   78.23     .06       0   118.3     .08       0  137.23     .06       0
  187.74     .08       0  193.41     .12       0   198.3    .045       0
   213.3     .12       0  222.46    .016       0  257.18     .06       0
   291.9     .08       0  305.77     .06       0  361.35     .08       0
  361.95     .12       0  396.07     .08       0  418.13     .06       0
#XS Ineff= 2 , 0
          170.65  790.57  232.44           790.5
Permanent Ineff=
       F       F
Bank Sta=198.74,214.19
XS Rating Curve= 0 ,0
Exp/Cntr=0.3,0.1

Type RM Length L Ch R = 1 ,76.8    ,61.9,61.7,61.6
XS GIS Cut Line= 2
     1759806.658      361322.676     1759534.286      361650.569
#Sta/Elev= 30
       0  791.34    8.32791.6596   21.42791.3292    39.8  791.01    55.8  790.03
   67.64789.7935  113.86  788.32  160.08788.2186   183.2  787.57   191.2  786.76
  200.31785.0685  206.31784.0179   208.9  783.46   215.1  782.08   219.1  781.74
   223.9  782.88  226.83  783.46   227.1  784.15   231.1  785.57     235  785.96
     239  785.76     247  787.27  252.53787.7527   298.8  788.29   354.6  787.07
   366.5  787.46   382.4  787.25   392.3787.7477   410.3   790.3   426.3  790.95
#Mann= 12 ,-1 , 0
       0     .12       0    8.32     .08       0   21.42     .12       0
   67.64     .06       0  113.86     .12       0  160.08     .06       0
  200.31     .12       0  206.31    .016       0   208.9    .045       0
   223.9    .016       0  252.53     .06       0   392.3     .12       0
#XS Ineff= 2 , 0
                          284.41          788.92
Permanent Ineff=
       F       F
Bank Sta=208.9,226.83
XS Rating Curve= 0 ,0
Exp/Cntr=0.3,0.1

Type RM Length L Ch R = 1 ,15      ,17.3,15,12.8
XS GIS Cut Line= 2
     1759760.461      361279.479     1759488.878      361611.578
#Sta/Elev= 30
       0  786.35    11.9  785.42    23.8  781.14   25.92781.0393   41.96781.3043
    71.5   781.4    87.4  780.37   119.2  782.93   135.1  781.29   162.9   782.8
   178.8  781.54   190.7  782.26   202.6  781.13     219  780.42  220.51   780.3
     234  780.07   238.3  780.22   278.1  779.77   305.9  780.16   329.7  781.17
   337.6  780.34   345.6  780.21   365.4  780.92   377.4  782.68   389.3  781.58
   401.2  782.81  407.47784.1935  415.19 785.236   421.1  785.79     429   785.7
#Mann= 7 ,-1 , 0
       0     .04       0   25.92     .12       0   41.96     .04       0
     219    .045       0     234     .04       0  407.47     .12       0
  415.19     .04       0
#XS Ineff= 2 , 0
          160.81  783.02  330.06          781.77
Permanent Ineff=
       F       F
Bank Sta=220.51,238.3
XS Rating Curve= 0 ,0
Exp/Cntr=0.3,0.1

Chan Stop Cuts=-1
Use User Specified Reach Order=0
Composite Channel Slope=5